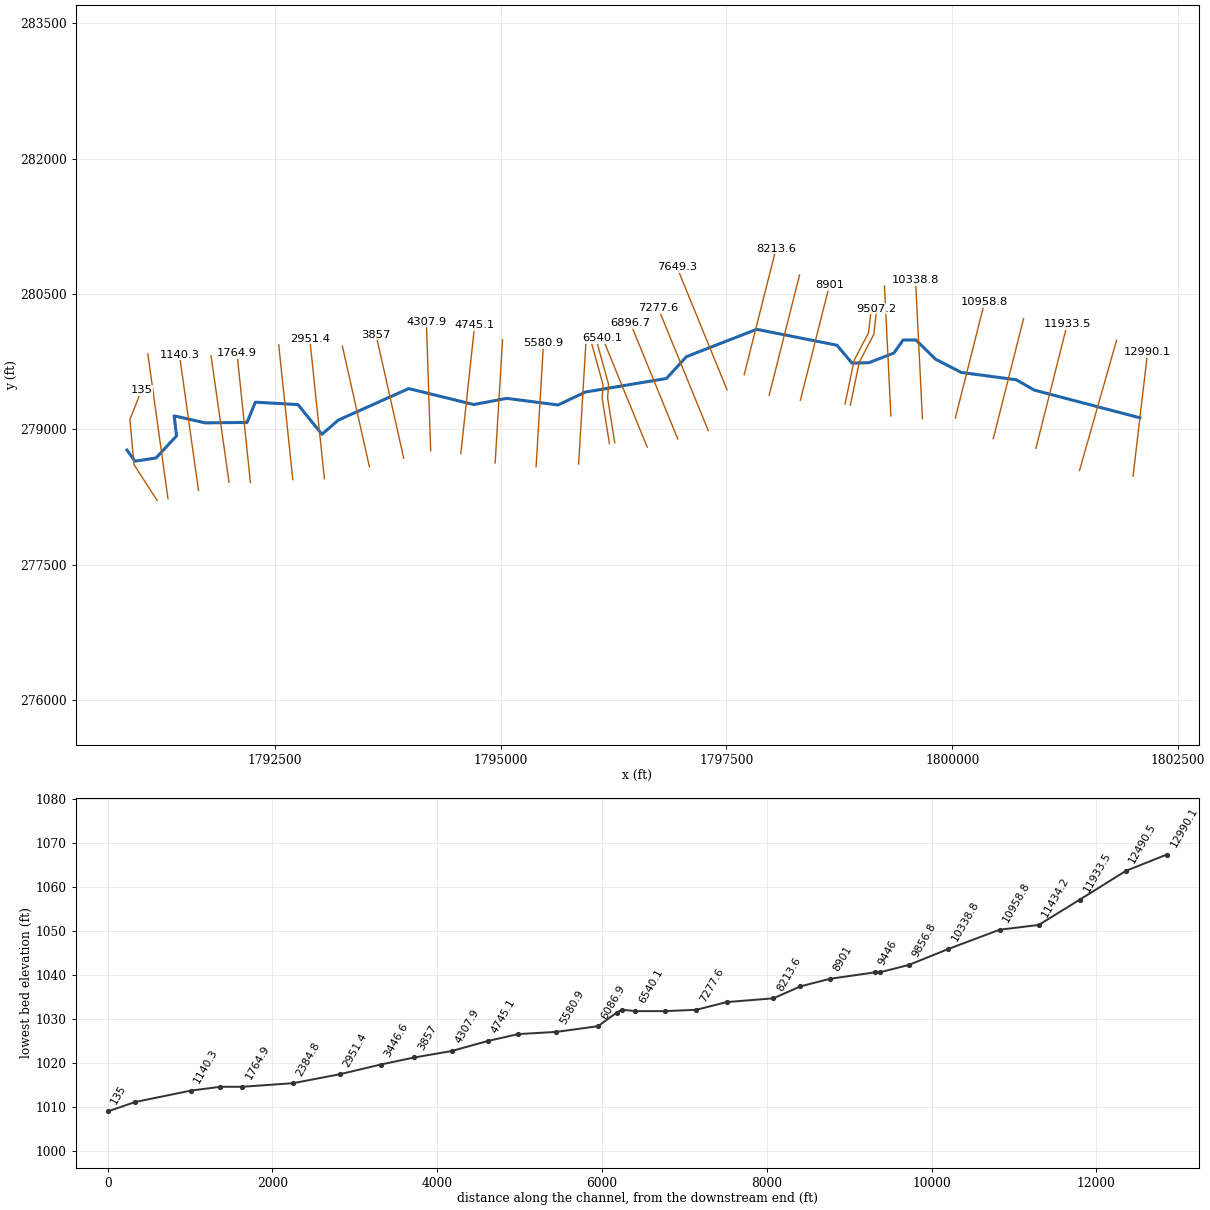
--- RFSmpsonCk.prj (project) ---

Proj Title=RFSmpsonCk
Current Plan=p01
Default Exp/Contr=0,0
English Units
Geom File=g01
Flow File=f01
Plan File=p01
BEGIN DESCRIPTION:
END DESCRIPTION:
DSS Export Rating Curves= 0
DSS Export Rating Curve Sorted= 0
DSS Export Volume Flow Curves= 0
DXF OffsetX= 0
DXF OffsetY= 0
DXF ScaleX= 0
DXF ScaleY= 0

--- RFSmpsonCk.p01 (plan) ---

Plan Title=Floodplain
Program Version=4.00
Geom File=g01
Flow File=f01
K Sum by GR=0
Std Step Tol=0.01
Critical Tol=0.01
Num of Std Step Trials=20
Max Error Tol=0.3
Flow Tol Ratio=0.001
Split Flow NTrial=30
Split Flow Tol=0.02
Split Flow Ratio=0.02
Log Output Level=0
Friction Slope Method=1
Unsteady Friction Slope Method=2
Unsteady Bridges Friction Slope Method=1
Global Log Level=0
CheckData=False
Run HTab=0
Run UNet=0
Run PostProcess=0
UNET Theta=0
UNET Theta Warmup=0
UNET ZTol=0
UNET ZSATol=0
UNET MxIter=0
UNET MaxInSteps=0
UNET DtIC=0
UNET DtMin=0
UNET MaxCRTS=0
UNET WFStab=0
UNET SFStab=0
UNET WFX=0
UNET SFX=0
UNET DSS MLevel=0
UNET DZMax Abort=0
UNET Convert EG Bridges=0
UNET Use Existing IB Tables=0
UNET Froude Limit=0
UNET Froude Power=0
Write IC File=0
Echo Input=False
Echo Output=False
Write Detailed=0

--- RFSmpsonCk.f01 (steady flow) ---

Flow Title=NFF Regression Equation
Program Version=4.10
Number of Profiles= 1
Profile Names=P100yr
River Rch & RM=RFSmpsonCk,Main            ,12990.1
    1158
River Rch & RM=RFSmpsonCk,Main            ,9856.8
    1270
River Rch & RM=RFSmpsonCk,Main            ,8901
    2074
River Rch & RM=RFSmpsonCk,Main            ,7649.3
    2630
River Rch & RM=RFSmpsonCk,Main            ,469.7
    2869
Boundary for River Rch & Prof#=RFSmpsonCk,Main            , 1
Up Type= 0
Dn Type= 3
Dn Slope=0.003936
DSS Import GetInterval= 0
DSS Import GetPeak= 0
DSS Import FillOption= 0

--- RFSmpsonCk.g01 (geometry) ---

Geom Title=USGS 10m DEM
Program Version=4.10

River Reach=RFSmpsonCk      ,Main
Reach XY= 30
     1802077.161      279127.072     1800909.061      279433.675
     1800707.566       279549.06     1800101.208      279629.472
     1799816.196      279776.004     1799597.433      279989.799
     1799454.993      279988.693     1799353.751      279844.945
     1799077.403      279737.916      1798889.76      279734.087
     1798723.209      279931.873     1797834.756      280107.679
     1797056.818      279804.504     1796836.217      279563.046
     1795940.373      279412.929     1795635.627      279269.352
     1795067.393      279342.573      1794703.25      279273.941
     1793982.964      279450.963     1793202.811       279101.13
     1793022.743      278944.133     1792757.399      279273.459
      1792285.41      279300.267     1792193.844      279075.584
     1791730.029      279071.137     1791386.724       279148.65
     1791413.263      278927.033     1791186.879      278682.427
     1790953.541      278646.358     1790864.255      278769.232

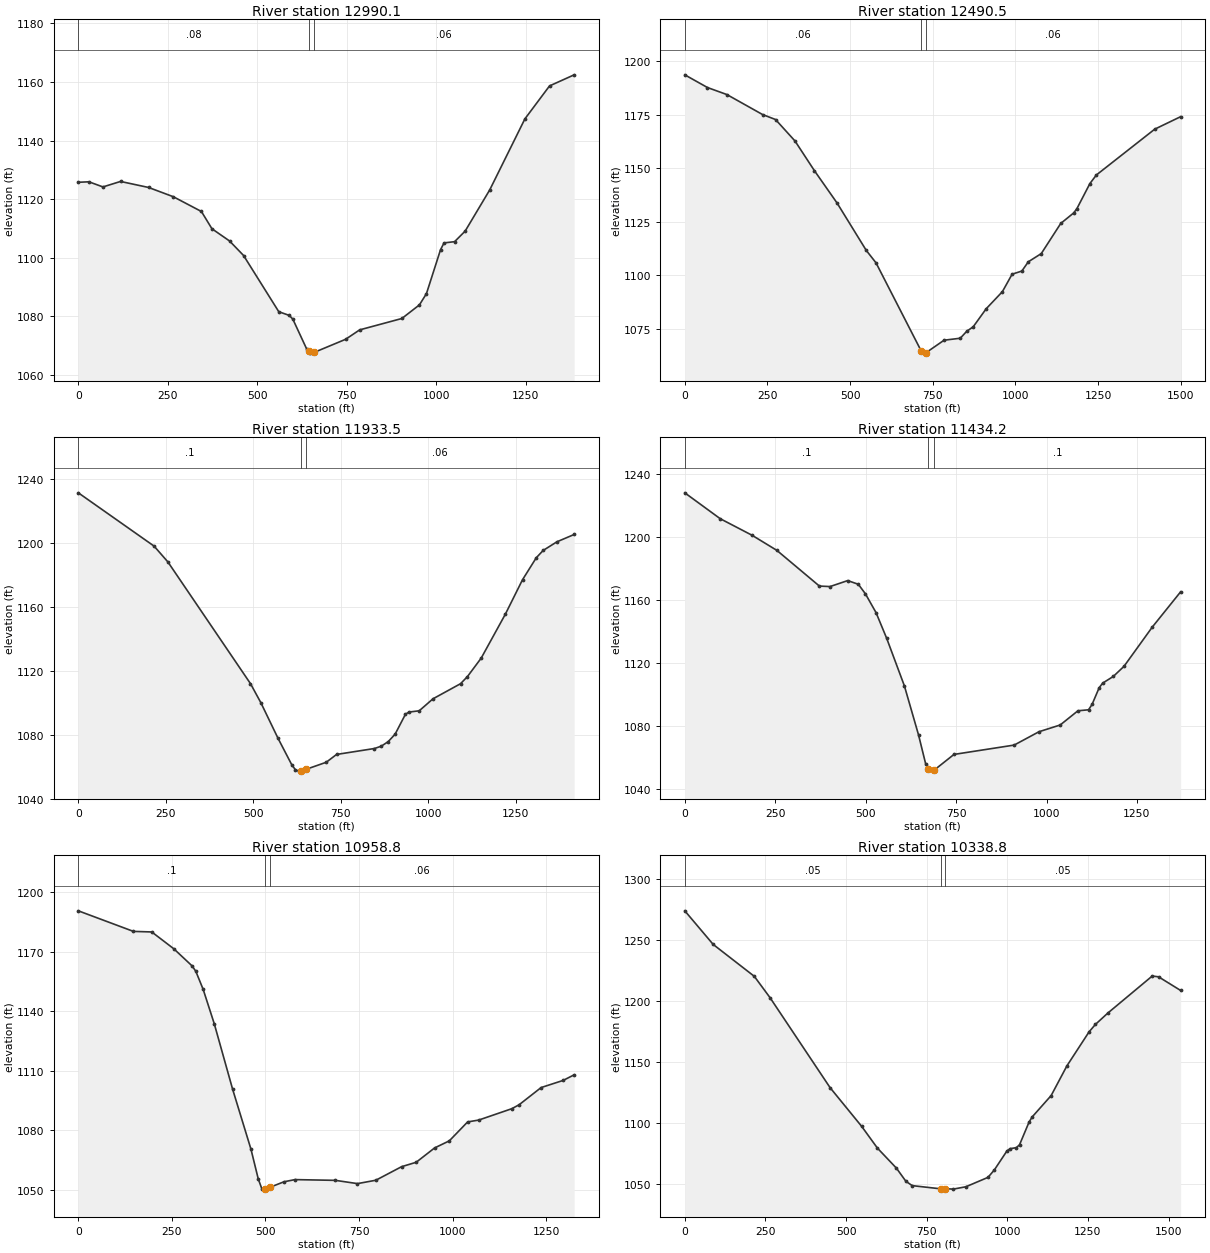
Type RM Length L Ch R = 1 ,12990.1 ,507.2,499.6,490.7
XS GIS Cut Line= 2
     1802001.323      278480.387     1802162.623       279855.92
#Sta/Elev= 30
       0 1125.76    29.5 1125.92    68.8 1124.17   117.9 1126.04   196.4 1123.98
   265.2 1120.83   343.8 1115.78   373.2 1109.88   422.4 1105.71   461.6 1100.74
   559.9 1081.55   589.3 1080.28   599.2    1079   638.5 1068.64   643.6 1067.99
   648.3  1067.4   658.6 1067.64   746.5 1072.12   785.8 1075.34   903.7 1079.23
   952.8 1083.88   972.4 1087.72  1011.7 1102.71  1021.5 1105.05    1051 1105.47
  1080.5 1109.08  1149.2 1123.16  1247.4 1147.41  1316.2 1158.67    1385 1162.46
#Mann= 3 , 0 , 0
       0     .08       0   643.6    .045       0   658.6     .06       0
Bank Sta=643.6,658.6
XS Rating Curve= 0 ,0
Exp/Cntr=0.3,0.1

Type RM Length L Ch R = 1 ,12490.5 ,556.2,556.9,557.6
XS GIS Cut Line= 2
      1801408.51      278543.047     1801818.857      279985.952
#Sta/Elev= 30
       0 1193.56    68.6 1187.63   127.5 1184.34   235.3 1175.02   274.5  1172.7
   333.4 1162.68   392.2 1148.81   460.8  1133.7   549.1 1111.59   578.5 1105.81
   714.5 1064.88   725.6 1063.66   729.5 1063.83   784.4 1069.69   833.4 1070.61
     853 1073.86   872.6 1075.96   911.8 1084.36   960.9 1092.36   990.3 1100.51
  1019.7 1101.97  1039.3 1106.29  1078.5 1110.12  1137.4 1124.19  1176.6  1129.1
  1186.4 1131.13  1225.6  1142.8  1245.2 1146.81  1421.7 1168.19  1500.1 1174.02
#Mann= 3 , 0 , 0
       0     .06       0   714.5    .045       0   729.5     .06       0
Bank Sta=714.5,729.5
XS Rating Curve= 0 ,0
Exp/Cntr=0.3,0.1

Type RM Length L Ch R = 1 ,11933.5 ,499.2,499.3,499.1
XS GIS Cut Line= 2
     1800925.815      278788.257     1801272.199      280162.262
#Sta/Elev= 30
       0 1231.46   216.5 1198.08   255.8 1188.22     492 1111.94   521.5 1100.07
   570.7 1077.71   610.1 1061.07   619.9 1058.16   629.8 1057.15   636.7 1057.33
   651.7 1058.34   708.5  1062.7     738  1067.6   846.3 1071.32   865.9 1072.79
   885.6 1075.64   905.3 1080.29   934.8 1092.75   944.7 1094.14   974.2 1094.94
  1013.5 1102.44  1092.3 1111.91    1112 1116.36  1151.3 1127.93  1220.2 1155.38
  1269.4 1177.02  1308.8 1190.81  1328.4 1195.37  1367.8 1200.79    1417 1205.37
#Mann= 3 , 0 , 0
       0      .1       0   636.7    .045       0   651.7     .06       0
Bank Sta=636.7,651.7
XS Rating Curve= 0 ,0
Exp/Cntr=0.3,0.1

Type RM Length L Ch R = 1 ,11434.2 ,475.3,475.4,475.4
XS GIS Cut Line= 2
     1800453.895      278895.916     1800789.009      280225.161
#Sta/Elev= 30
       0 1227.79    97.9 1211.39     186 1200.89   254.6  1191.3   372.1 1168.69
   401.5 1168.38   450.4 1172.16   479.8 1169.82   499.4 1163.76   528.8 1151.82
   558.1 1135.59   607.1 1105.43   646.2 1074.35   665.8 1056.11   673.7 1052.61
   685.4 1051.39   688.7 1051.89   744.2 1061.98   910.6  1067.9   979.2 1076.36
  1037.9 1080.64  1086.9 1089.64  1116.2 1090.27    1126 1093.68  1145.6 1104.26
  1155.4 1107.19  1184.8 1111.43  1214.2  1117.8  1292.5 1142.71  1370.8 1165.04
#Mann= 3 , 0 , 0
       0      .1       0   673.7    .045       0   688.7      .1       0
Bank Sta=673.7,688.7
XS Rating Curve= 0 ,0
Exp/Cntr=0.3,0.1

Type RM Length L Ch R = 1 ,10958.8 ,612.7,620.1,677
XS GIS Cut Line= 2
     1800034.059      279125.103     1800357.901      280409.588
#Sta/Elev= 30
       0 1190.59   147.2 1180.22   196.2 1179.94   255.1 1171.45   304.2 1162.78
     314 1160.06   333.6 1150.94   363.1 1133.72   412.1 1100.73   461.2 1070.44
   480.8 1055.37   490.6  1050.3     498 1050.34     513  1051.3   549.5 1054.01
   578.9  1055.1   686.9 1054.72   745.8 1053.08   794.8 1054.78   863.5  1061.6
   902.7 1063.84   951.8 1071.06   991.1 1074.63  1040.1 1084.18  1069.6 1085.11
  1157.9 1090.83  1177.5 1092.81  1236.4  1101.5  1295.2  1105.1  1324.7 1107.92
#Mann= 3 , 0 , 0
       0      .1       0     498    .045       0     513     .06       0
Bank Sta=498,513
XS Rating Curve= 0 ,0
Exp/Cntr=0.3,0.1

Type RM Length L Ch R = 1 ,10338.8 ,483.2,482,427.4
XS GIS Cut Line= 2
     1799669.517      279117.129     1799593.783      280652.878
#Sta/Elev= 30
       0  1273.7    88.1 1246.18   215.5  1220.1   264.4  1202.6   450.5    1129
   548.4 1097.32   597.4 1079.48   656.2 1063.13   685.6 1052.35   705.2  1048.8
   793.4 1046.18   808.4 1046.32   832.5 1045.93   871.6 1047.86   940.2 1055.55
   959.8 1061.59     999 1077.19  1008.8 1079.04  1028.3 1079.88  1038.1 1082.26
  1067.5 1100.76  1077.3 1105.04  1136.1 1122.51    1185 1146.83  1253.6 1174.62
  1273.2 1180.69  1312.4 1190.15  1449.5 1220.32  1469.1 1219.71  1537.6 1208.53
#Mann= 3 , 0 , 0
       0     .05       0   793.4    .045       0   808.4     .05       0
Bank Sta=793.4,808.4
XS Rating Curve= 0 ,0
Exp/Cntr=0.3,0.1

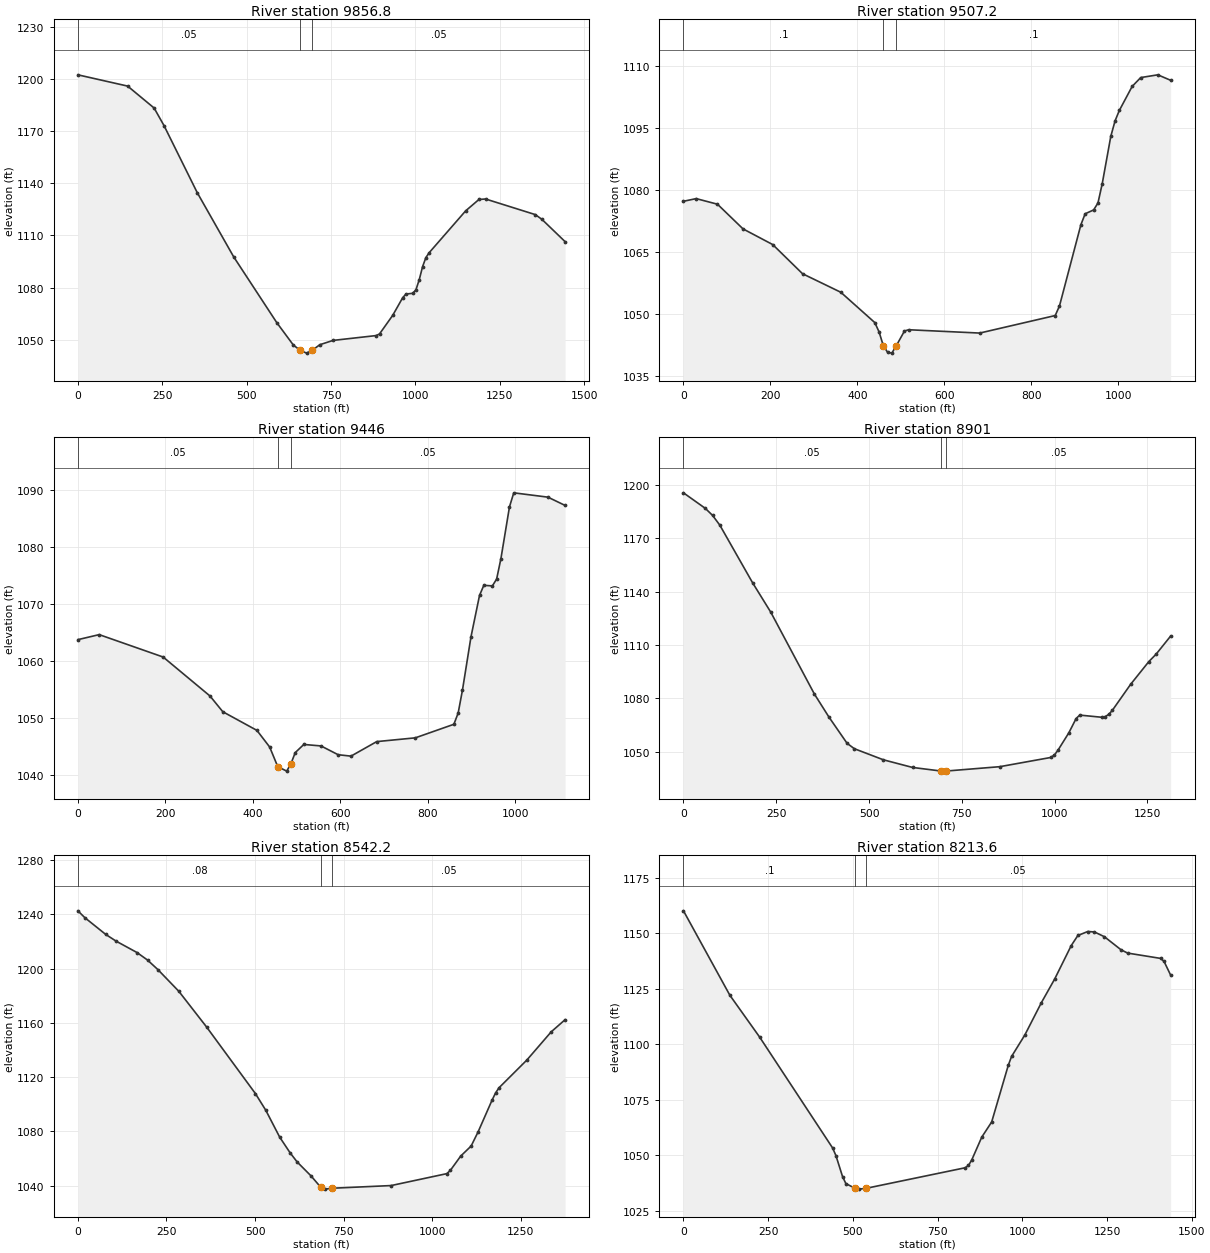
Type RM Length L Ch R = 1 ,9856.8  ,355.2,349.6,340
XS GIS Cut Line= 2
     1799320.834      279147.465     1799249.696      280588.816
#Sta/Elev= 30
       0  1202.4   147.3 1195.92   225.8 1183.29   255.2 1173.15   353.4 1134.65
   461.4  1097.7     589 1059.86   638.1 1046.96   657.7    1044   677.4 1042.29
   694.3 1043.94   716.6 1047.13   755.9 1049.61   883.5 1052.39   893.4 1053.32
   932.6 1064.05   962.1 1074.19   971.9 1076.29   991.5  1076.7  1001.3  1078.7
  1011.2 1084.62    1021 1092.05  1030.8 1097.26  1040.6 1100.09  1148.6 1124.15
  1187.9 1130.68  1207.5 1130.97  1354.8 1121.99  1374.4 1119.27  1443.1 1106.43
#Mann= 3 , 0 , 0
       0     .05       0   657.7    .045       0   694.3     .05       0
Bank Sta=657.7,694.3
XS Rating Curve= 0 ,0
Exp/Cntr=0.3,0.1

Type RM Length L Ch R = 1 ,9507.2  ,61.3,61.2,64.8
XS GIS Cut Line= 4
      1798871.59      279266.586     1798971.433      279745.146
     1799131.823       280051.98       1799163.7      280335.331
#Sta/Elev= 30
       0 1077.26    29.3  1077.9    78.2 1076.55   136.9  1070.6   205.3 1066.81
   273.8 1059.78   361.8 1055.31     440 1047.99   449.8 1045.74   459.5 1042.43
   469.3 1040.83   479.1 1040.63   488.9 1042.33   508.1 1045.96   517.7 1046.27
   681.2 1045.47   854.8  1049.7   864.6 1052.02   913.8  1071.6   923.6 1074.24
   943.2 1075.18   953.1 1076.86   962.9 1081.52   982.6 1092.94   992.4 1096.66
  1002.2 1099.17  1031.7 1104.97  1051.4  1107.1  1090.7 1107.76  1120.2 1106.44
#Mann= 3 , 0 , 0
       0      .1       0   459.5    .045       0   488.9      .1       0
Bank Sta=459.5,488.9
XS Rating Curve= 0 ,0
Exp/Cntr=0.3,0.1

Type RM Length L Ch R = 1 ,9446    ,545.9,544.9,543.9
XS GIS Cut Line= 4
     1798812.854       279278.84       1798914.4      279765.557
     1799073.454      280069.834     1799104.077      280342.039
#Sta/Elev= 30
       0 1063.68    48.7 1064.56     195 1060.63   302.2 1053.79   331.5 1051.03
   409.5 1047.76   438.7 1044.84   457.2 1041.39   477.7 1040.61   487.4 1041.92
   497.2 1043.86   516.8 1045.29   556.1 1045.03   595.3 1043.49   624.7 1043.24
   683.6 1045.79   771.9 1046.45   860.1 1048.83   869.9  1050.8   879.7 1054.81
   899.2 1064.16   918.8 1071.45   928.6 1073.21   948.2 1073.11   957.9 1074.31
   967.7 1077.89   987.3 1086.98   997.1 1089.44  1075.3 1088.68  1114.5 1087.23
#Mann= 3 , 0 , 0
       0     .05       0   457.2    .045       0   487.4     .05       0
Bank Sta=457.2,487.4
XS Rating Curve= 0 ,0
Exp/Cntr=0.3,0.1

Type RM Length L Ch R = 1 ,8901    ,358.7,358.9,358.7
XS GIS Cut Line= 2
     1798318.849      279321.703     1798639.883      280594.354
#Sta/Elev= 30
       0 1195.61    58.8 1186.88    78.4 1182.92      98 1177.42   186.1 1145.08
   235.1 1128.55   352.6 1082.53   391.8 1069.58   440.8 1054.78   460.4 1051.75
   538.7 1045.51   617.1 1041.22   693.3 1039.22   705.2 1039.15   708.3 1039.21
   852.2 1041.65   989.3 1046.82   999.1 1048.13  1008.9  1050.9  1038.3 1060.72
  1057.8 1068.72  1067.6 1070.65  1126.4 1069.44  1136.2 1069.79    1146 1071.08
  1155.8 1073.44  1204.8 1087.99  1253.8 1100.75  1273.3  1104.9  1312.5 1115.09
#Mann= 3 , 0 , 0
       0     .05       0   693.3    .045       0   708.3     .05       0
Bank Sta=693.3,708.3
XS Rating Curve= 0 ,0
Exp/Cntr=0.3,0.1

Type RM Length L Ch R = 1 ,8542.2  ,329.6,328.6,327.8
XS GIS Cut Line= 2
     1797973.259      279377.088     1798309.729      280710.537
#Sta/Elev= 30
       0 1242.67    19.6 1237.62    78.6 1225.26     108 1220.29     167 1211.89
   196.5 1206.37   225.9  1199.3   284.9 1183.32   363.5 1156.91     501 1107.92
   530.4 1095.57   569.7 1075.72   599.2 1064.13   618.9 1057.46   658.2 1047.13
   685.8 1038.71   697.4 1037.42   717.1 1038.07   884.1 1040.05  1041.3 1048.84
  1051.1 1051.16  1080.6  1061.8    1110  1069.2  1129.7 1079.66    1169 1103.01
  1178.8 1108.27  1188.6 1112.15  1267.2  1132.6    1336 1153.42  1375.2 1162.38
#Mann= 3 , 0 , 0
       0     .08       0   685.8    .045       0   717.1     .05       0
Bank Sta=685.8,717.1
XS Rating Curve= 0 ,0
Exp/Cntr=0.3,0.1

Type RM Length L Ch R = 1 ,8213.6  ,548.9,564.2,579.3
XS GIS Cut Line= 2
     1797697.114      279606.084      1798049.02      281000.332
#Sta/Elev= 30
       0 1160.15     137 1122.08     225  1103.2   440.2 1053.26     450 1049.83
   469.5 1040.38   479.3 1037.23   507.1 1035.01   518.4 1034.71     538 1035.04
   831.5 1044.34   841.3 1045.37     851  1047.9   880.4 1058.13   909.7 1064.98
   958.6 1090.46   968.4  1094.5  1007.6 1104.18  1056.5 1118.78  1095.6 1129.39
  1144.5 1144.47  1164.1 1149.03  1193.4 1150.83    1213 1150.63  1242.3 1148.49
  1291.2 1142.63  1310.8 1141.11  1408.6  1138.7  1418.4 1137.37    1438 1131.16
#Mann= 3 , 0 , 0
       0      .1       0   507.1    .045       0     538     .05       0
Bank Sta=507.1,538
XS Rating Curve= 0 ,0
Exp/Cntr=0.3,0.1

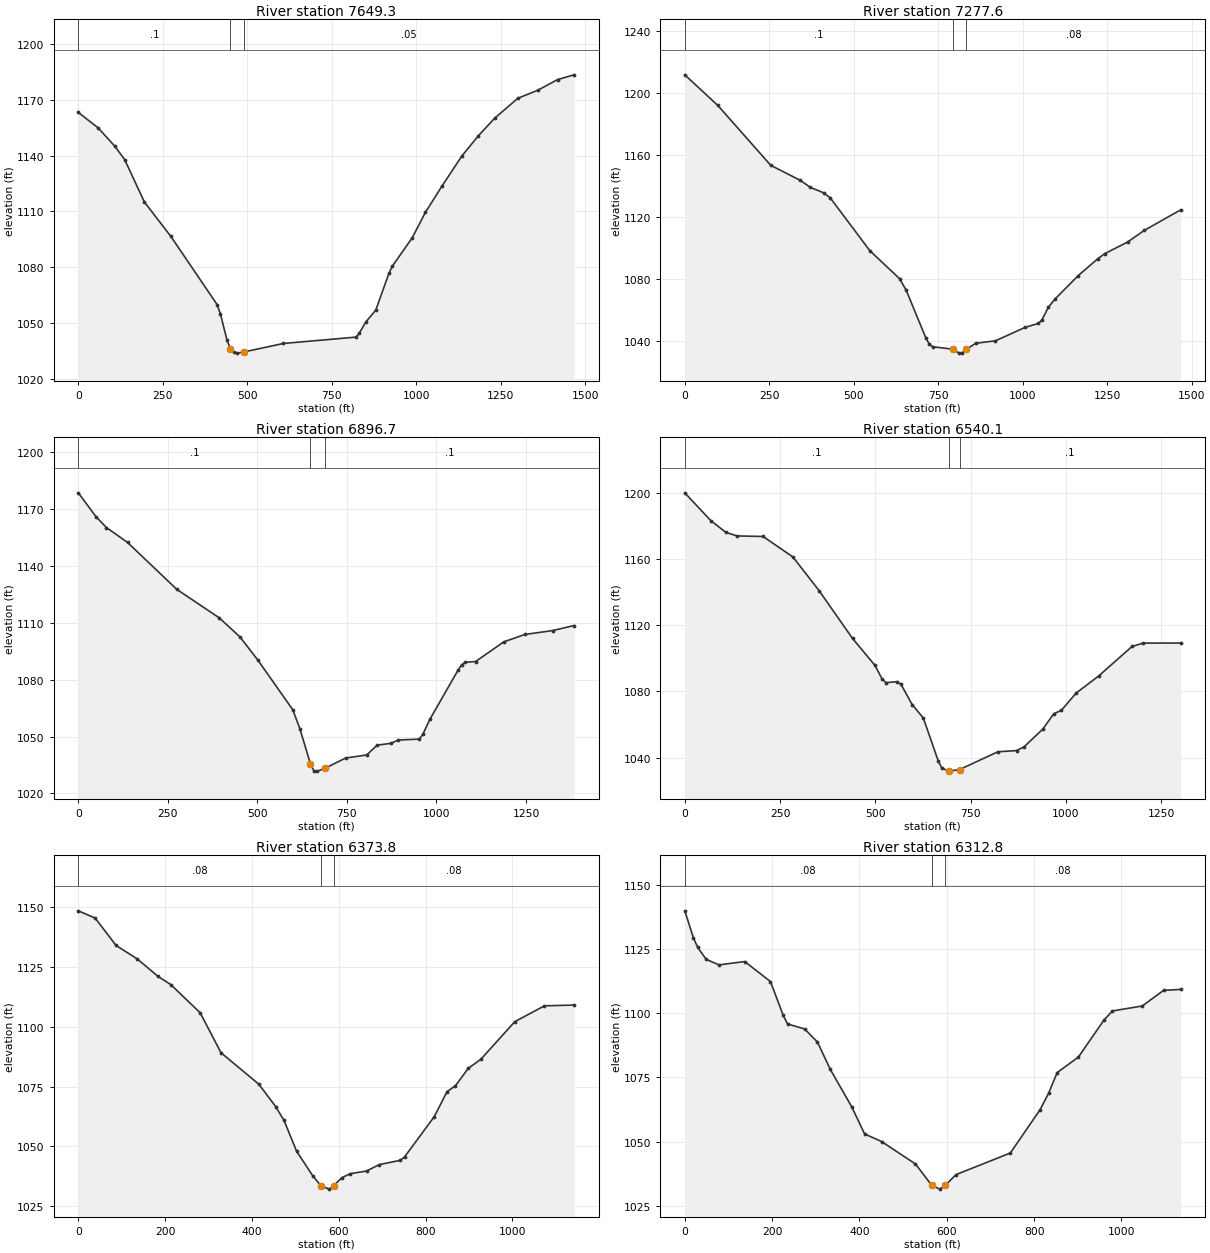
Type RM Length L Ch R = 1 ,7649.3  ,373.6,371.7,371.1
XS GIS Cut Line= 2
     1797507.086      279437.191     1796952.475      280795.682
#Sta/Elev= 30
       0 1163.16    58.7 1154.85   107.6 1145.09     137 1137.86   195.6 1115.03
   273.9 1096.55   410.9  1059.9   420.6 1054.85   440.2 1040.77     450 1036.28
   459.8  1034.3   469.6 1033.86   489.1 1034.45   606.5 1039.04   821.7 1042.46
   831.5 1044.55   851.1 1050.67   880.4 1056.96   919.5 1076.82   929.3 1080.57
     988 1095.72  1027.1 1109.42    1076  1123.5  1134.7 1139.63  1183.7 1150.55
  1232.6 1160.12    1301 1170.78  1359.7 1175.05  1418.4  1180.8  1467.3 1183.36
#Mann= 3 , 0 , 0
       0      .1       0     450    .045       0   489.1     .05       0
Bank Sta=450,489.1
XS Rating Curve= 0 ,0
Exp/Cntr=0.3,0.1

Type RM Length L Ch R = 1 ,7277.6  ,379,381,381.6
XS GIS Cut Line= 2
     1797298.752      278985.802     1796744.142      280344.293
#Sta/Elev= 30
       0 1211.45    97.8 1191.72   254.3 1153.16   342.4 1143.37   371.7 1138.91
   410.9 1135.41   430.4 1132.19   547.8 1098.09   635.8 1080.06   655.4 1072.58
   714.1 1041.56   723.9 1037.88   733.7 1036.21   792.4 1034.66   811.9  1032.1
   821.7 1032.43   833.2 1034.44   860.8 1038.46   919.5 1040.03  1007.6 1048.73
  1046.7 1051.25  1056.5 1053.31    1076 1061.63  1095.6 1066.93  1164.1 1081.97
  1222.8 1093.01  1242.4 1096.14  1310.8 1103.72  1359.7 1111.16  1467.3 1124.38
#Mann= 3 , 0 , 0
       0      .1       0   792.4    .045       0   833.2     .08       0
Bank Sta=792.4,833.2
XS Rating Curve= 0 ,0
Exp/Cntr=0.3,0.1

Type RM Length L Ch R = 1 ,6896.7  ,356,356.6,356.4
XS GIS Cut Line= 2
     1796960.984      278894.081     1796437.548      280175.472
#Sta/Elev= 30
       0 1178.66    49.1 1166.13    78.5 1160.33   137.4 1152.48   274.9 1127.72
   392.7 1112.79   451.6 1102.59   500.7 1090.53   598.8  1064.2   618.5 1054.22
   647.9 1035.79   657.7 1031.96   667.6  1031.8   689.4 1033.35   746.1  1038.7
     805 1040.32   834.4  1045.5   873.7 1046.51   893.3 1048.22   952.2  1048.7
     962 1051.26   981.7 1059.19  1060.2 1085.08    1070 1087.81  1079.9  1089.2
  1109.3 1089.65  1187.8    1100  1246.7 1103.91  1325.3    1106  1384.2 1108.64
#Mann= 3 , 0 , 0
       0      .1       0   647.9    .045       0   689.4      .1       0
Bank Sta=647.9,689.4
XS Rating Curve= 0 ,0
Exp/Cntr=0.3,0.1

Type RM Length L Ch R = 1 ,6540.1  ,177.2,166.3,156
XS GIS Cut Line= 2
     1796623.216      278802.361     1796130.955      280006.651
#Sta/Elev= 30
       0 1199.86    68.5 1183.02   107.6 1176.03     137 1173.84   205.4  1173.5
   283.7 1161.14   352.2 1140.86   440.2 1111.92   498.9  1095.7   518.4 1087.23
   528.2 1085.22   557.6 1085.84   567.4  1084.2   596.7 1071.98     626 1063.87
   665.2  1037.9     675 1033.49   694.5  1031.8   721.3 1032.78   821.7 1043.49
   870.6  1044.2   890.2 1046.44   939.1 1057.06   968.4 1066.45     988 1068.46
  1027.1 1078.96  1085.8 1089.18  1173.8 1107.11  1203.2 1109.12    1301 1109.15
#Mann= 3 , 0 , 0
       0      .1       0   694.5    .045       0   721.3      .1       0
Bank Sta=694.5,721.3
XS Rating Curve= 0 ,0
Exp/Cntr=0.3,0.1

Type RM Length L Ch R = 1 ,6373.8  ,60.9,60.9,61
XS GIS Cut Line= 4
     1796264.207      278850.361     1796184.888      279346.968
     1796195.423       279497.97     1796065.584      279968.197
#Sta/Elev= 30
       0 1148.57    38.7 1145.54      87 1134.07   135.4 1128.49   183.8  1121.1
   212.8 1117.74   280.5 1105.95   328.8 1089.18   415.9 1076.02   454.6 1066.69
   473.9 1060.86   502.9 1047.97   540.7 1037.52   559.7 1033.41   578.4 1032.13
     588 1033.52     607 1036.88   625.9 1038.57     664 1039.71   693.3 1042.39
   742.1  1044.2   751.8 1045.66   820.1 1062.48   849.4  1072.9   868.9 1075.39
   898.2 1082.64   927.4 1086.48  1005.5 1102.19  1073.8 1108.82  1142.1 1109.14
#Mann= 3 , 0 , 0
       0     .08       0   559.7    .045       0     588     .08       0
Bank Sta=559.7,588
XS Rating Curve= 0 ,0
Exp/Cntr=0.3,0.1

Type RM Length L Ch R = 1 ,6312.8  ,227,225.9,223.7
XS GIS Cut Line= 4
     1796204.958      278840.898     1796124.556       279344.29
     1796134.854        279491.9     1796007.748      279952.228
#Sta/Elev= 30
       0 1139.91    19.6 1129.46    29.4 1125.71      49 1120.99    78.4 1118.85
   137.2 1120.15   196.1 1112.37   225.5 1099.16   235.3 1095.83   274.5 1093.87
   303.9 1088.76   333.3 1078.09   382.3 1063.56   411.7 1052.99     451 1049.99
   528.3 1041.27   565.3 1033.01   583.8 1031.48   596.8 1032.93   620.8 1037.11
   745.5 1045.55   813.7 1062.44   833.2 1068.84   852.7 1076.88   901.4 1082.93
   959.9 1097.34   979.4 1100.91  1047.6 1102.83  1096.3 1108.91  1135.3 1109.29
#Mann= 3 , 0 , 0
       0     .08       0   565.3    .045       0   596.8     .08       0
Bank Sta=565.3,596.8
XS Rating Curve= 0 ,0
Exp/Cntr=0.3,0.1

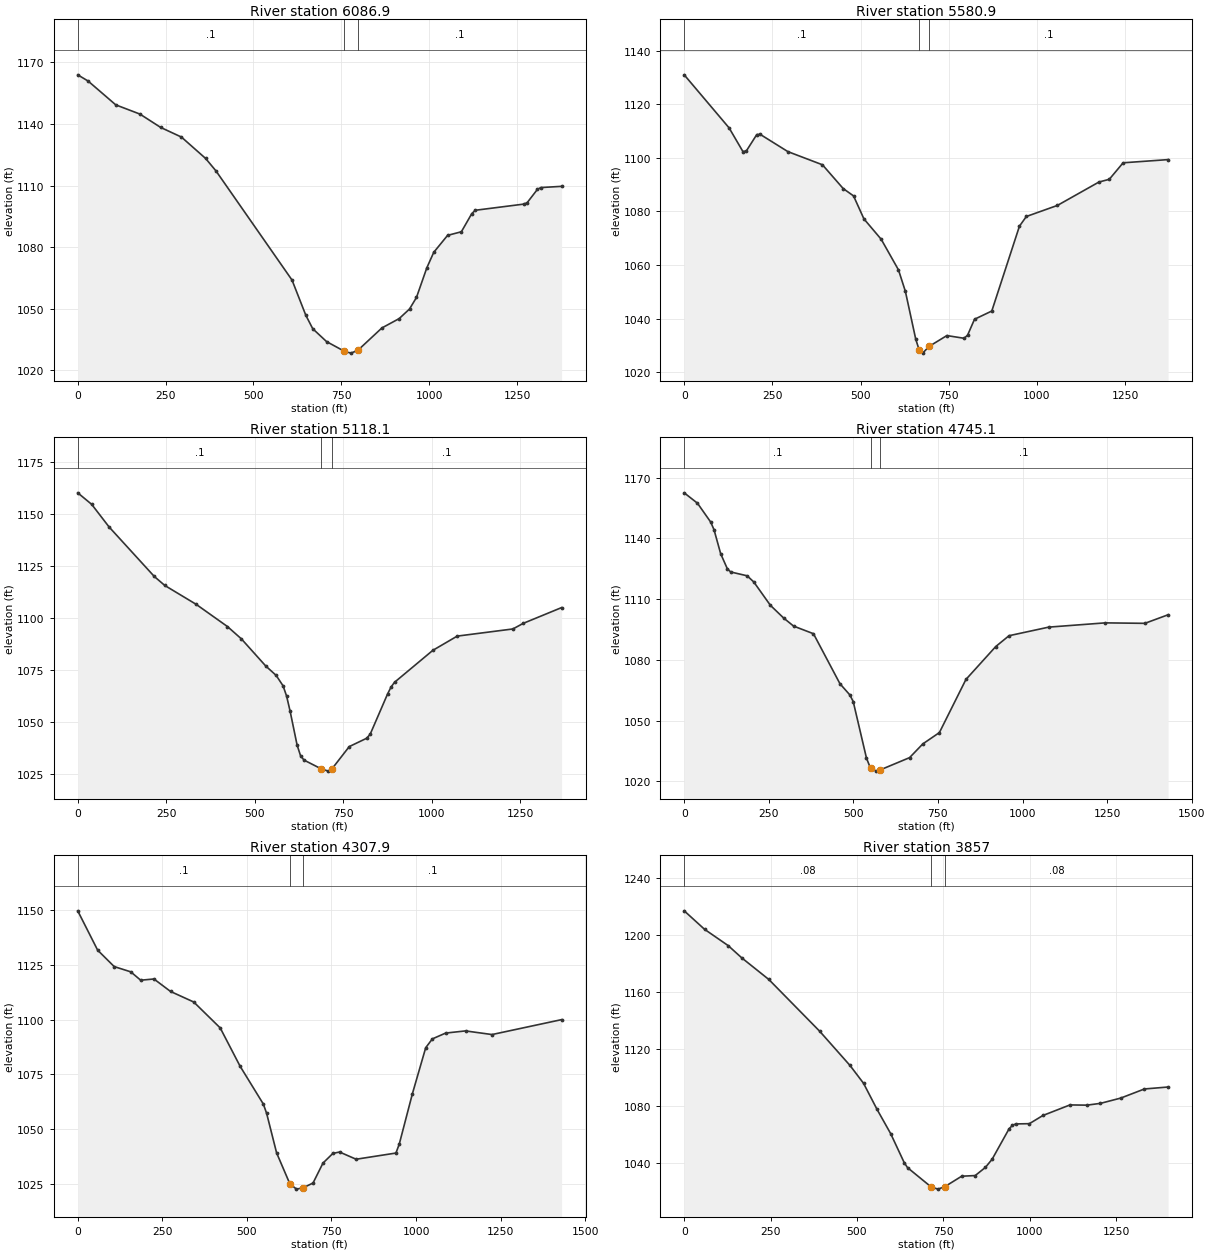
Type RM Length L Ch R = 1 ,6086.9  ,504.5,506,508.3
XS GIS Cut Line= 2
     1795864.063      278614.607     1795946.444      279988.845
#Sta/Elev= 30
       0 1163.96    29.5 1160.93   108.2 1149.33     177 1144.83     236 1138.33
     295 1133.64   363.8 1123.23   393.3 1117.15   609.7 1063.97     649 1046.79
   668.7 1040.25     708 1033.99   757.2 1029.42   776.9 1028.38   796.5 1029.67
   865.4 1040.65   914.5  1045.2     944 1049.88   963.7 1055.49   993.2 1069.94
  1012.9 1077.49  1052.2 1085.74  1091.5 1087.51    1121 1096.31  1130.9 1097.97
  1268.5 1100.97  1278.4 1101.61  1307.9 1108.17  1317.7 1109.04  1376.7 1109.63
#Mann= 3 , 0 , 0
       0      .1       0   757.2    .045       0   796.5      .1       0
Bank Sta=757.2,796.5
XS Rating Curve= 0 ,0
Exp/Cntr=0.3,0.1

Type RM Length L Ch R = 1 ,5580.9  ,463.2,462.9,462.5
XS GIS Cut Line= 2
      1795393.31      278585.803     1795475.412      279955.402
#Sta/Elev= 30
       0 1130.94   127.4 1111.12   166.6 1102.28   176.4 1102.57   205.8 1108.65
   215.6 1108.71     294 1102.28     392 1097.37   450.8  1088.5   480.2 1085.75
   509.6 1077.18   558.6 1069.57   607.6 1058.15   627.2 1050.12   656.6 1032.26
   666.4 1028.22   676.2 1027.08   694.6  1029.6   744.8 1033.63   793.8 1032.62
   803.6 1033.79   823.2 1039.72   872.2 1042.79   950.6 1074.45   970.2 1078.07
  1058.4 1082.21    1176 1090.93  1205.4 1091.95  1244.6 1098.11  1372.1  1099.3
#Mann= 3 , 0 , 0
       0      .1       0   666.4    .045       0   694.6      .1       0
Bank Sta=666.4,694.6
XS Rating Curve= 0 ,0
Exp/Cntr=0.3,0.1

Type RM Length L Ch R = 1 ,5118.1  ,373.8,372.9,372.1
XS GIS Cut Line= 2
     1794939.919      278626.444     1795021.743      279991.404
#Sta/Elev= 30
       0 1160.28    39.4 1154.75    88.5  1143.9   216.4 1120.09   245.9 1115.79
   334.5 1106.73     423 1096.05   462.4 1090.13   531.2  1077.1   560.7 1072.57
   580.4 1067.52   590.2 1062.63   600.1 1055.43   619.8 1039.17   629.6 1033.99
   639.4 1031.89   688.6 1027.63   708.3 1026.58   718.1  1027.6   767.3 1038.37
   816.5 1042.37   826.4  1044.3   875.5 1063.62   885.4 1066.98   895.2 1069.26
  1003.4  1084.6  1072.3 1091.44  1229.7 1094.88  1259.2 1097.59  1367.4 1105.15
#Mann= 3 , 0 , 0
       0      .1       0   688.6    .045       0   718.1      .1       0
Bank Sta=688.6,718.1
XS Rating Curve= 0 ,0
Exp/Cntr=0.3,0.1

Type RM Length L Ch R = 1 ,4745.1  ,432.7,437.2,441.7
XS GIS Cut Line= 2
     1794560.013      278729.617     1794713.152       280151.69
#Sta/Elev= 30
       0 1162.54    39.2 1157.41    78.4 1148.07    88.2 1144.28   107.8 1132.45
   127.4 1125.04   137.2 1123.44   186.1 1121.53   205.7 1118.49   254.7 1106.96
   293.9 1100.67   323.3 1096.68   382.1 1092.91   460.4 1068.19   489.8 1062.63
   499.6 1059.38   538.8 1031.42   550.8 1026.39   568.2    1025     578 1025.51
   666.2 1031.67   705.4 1038.47   754.3 1044.05   832.7 1070.29   920.9 1086.57
   960.1 1091.92  1077.6 1096.17  1244.2 1098.27  1361.7 1098.04  1430.3 1102.27
#Mann= 3 , 0 , 0
       0      .1       0   550.8    .045       0     578      .1       0
Bank Sta=550.8,578
XS Rating Curve= 0 ,0
Exp/Cntr=0.3,0.1

Type RM Length L Ch R = 1 ,4307.9  ,448.1,450.9,453.8
XS GIS Cut Line= 2
     1794226.209       278760.62       1794178.9      280190.132
#Sta/Elev= 30
       0 1149.54    58.8 1131.63   107.8 1124.13   156.7 1121.74   186.1 1117.92
   225.3 1118.48   274.3  1112.8   342.9 1107.99   421.2 1096.17     480  1078.7
   548.6 1061.49   558.4 1057.23   587.8 1039.25     627 1025.14   646.6 1022.72
   666.2 1023.31   695.6 1025.52   724.9 1034.59   754.3 1039.01   773.9 1039.63
   822.9 1036.34   940.5 1039.16   950.3 1043.18   989.4 1066.29  1028.6 1087.17
  1048.2 1091.18  1087.4 1093.83  1146.2 1094.82  1224.6 1093.16  1430.3 1099.96
#Mann= 3 , 0 , 0
       0      .1       0     627    .045       0   666.2      .1       0
Bank Sta=627,666.2
XS Rating Curve= 0 ,0
Exp/Cntr=0.3,0.1

Type RM Length L Ch R = 1 ,3857    ,410.3,410.4,410.4
XS GIS Cut Line= 2
     1793927.429      278680.558     1793621.822      280047.018
#Sta/Elev= 30
       0 1217.17    58.8 1204.18   127.3 1192.68   166.5 1184.07   244.8 1168.86
   391.7  1132.5   479.8 1108.31     519 1095.75   558.1 1077.36   597.3 1060.41
   636.5 1039.99   646.2  1036.4   714.8 1022.77   734.4 1021.27     754 1022.99
   802.9 1030.36   842.1 1030.82   871.5 1036.55     891  1042.3     940  1063.7
   949.8 1066.17   959.6 1067.17   998.8 1067.34  1037.9  1073.1  1116.3 1080.54
  1165.2 1080.38  1204.4 1081.64  1263.1 1085.35  1331.7 1091.77  1400.2 1093.15
#Mann= 3 , 0 , 0
       0     .08       0   714.8    .045       0     754     .08       0
Bank Sta=714.8,754
XS Rating Curve= 0 ,0
Exp/Cntr=0.3,0.1

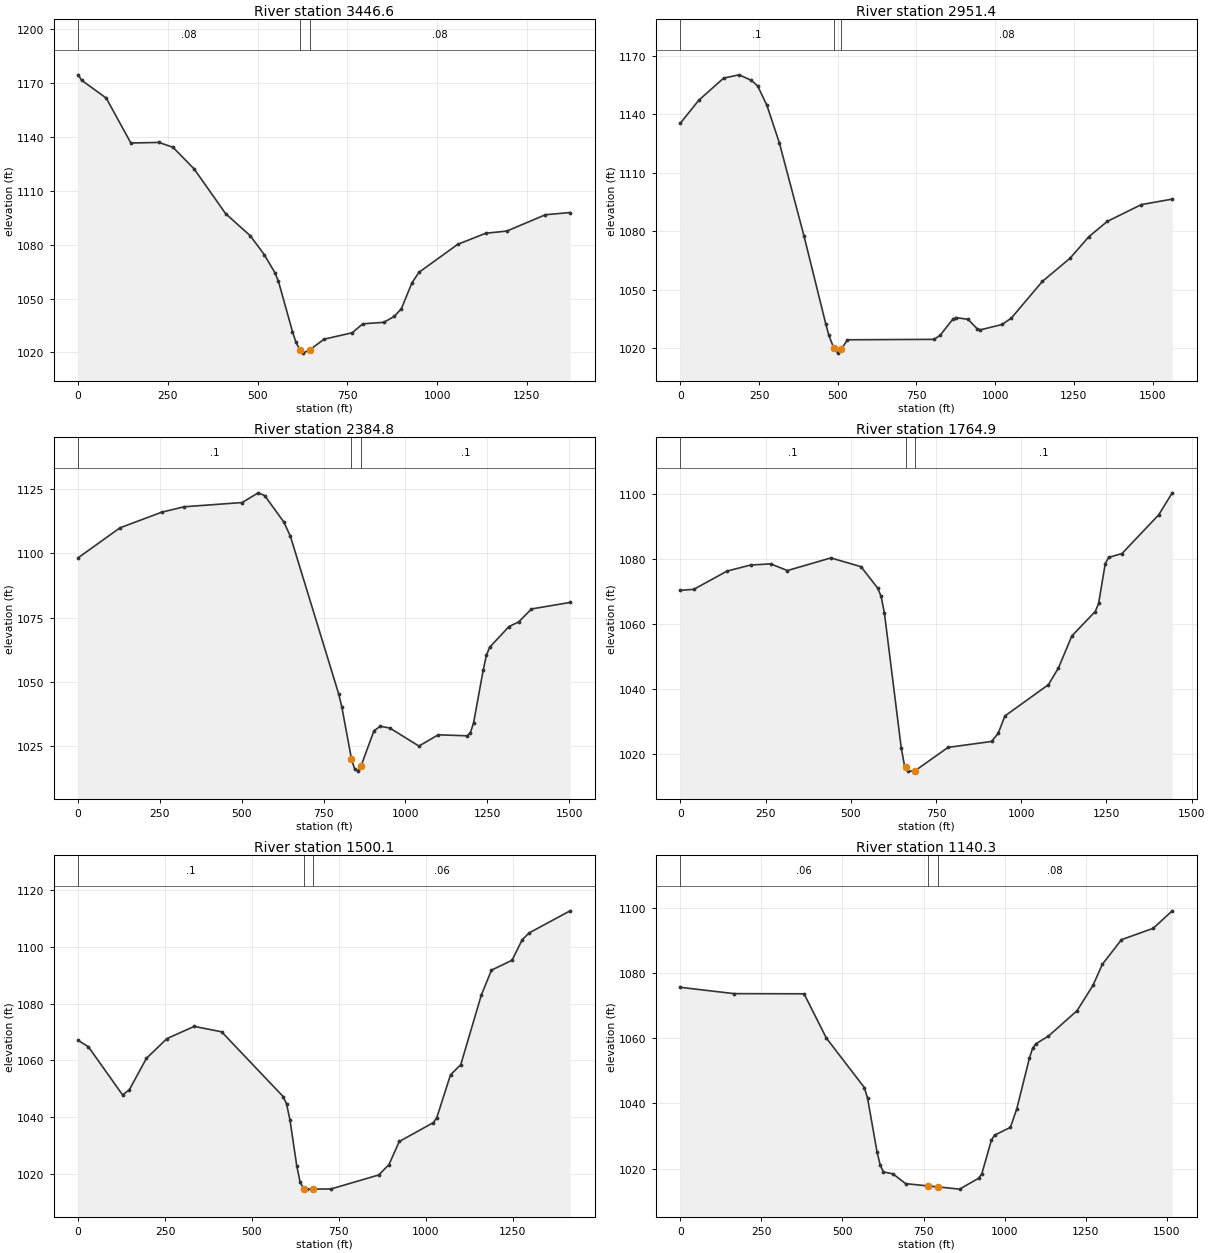
Type RM Length L Ch R = 1 ,3446.6  ,497.8,495.1,492.4
XS GIS Cut Line= 2
     1793548.277      278583.642     1793249.281       279920.76
#Sta/Elev= 30
       0 1174.44     9.8 1171.41    78.3  1161.5   146.8 1136.52   225.1 1136.84
   264.2 1134.14     323 1122.12     411 1097.18   479.6 1084.91   518.7 1074.34
   548.1 1064.36   557.8 1059.64     597 1031.64   606.8 1025.61   617.4 1021.54
   626.4 1019.65   645.9 1021.59   685.1 1027.41   763.4 1030.98   792.7 1035.95
   851.4 1036.78   880.8  1040.1   900.4 1044.41   929.7 1058.73   949.3  1064.6
    1057 1080.14  1135.3 1086.33    1194 1087.54  1301.6 1096.63  1370.1 1097.85
#Mann= 3 , 0 , 0
       0     .08       0   617.4    .045       0   645.9     .08       0
Bank Sta=617.4,645.9
XS Rating Curve= 0 ,0
Exp/Cntr=0.3,0.1

Type RM Length L Ch R = 1 ,2951.4  ,566.4,566.7,566
XS GIS Cut Line= 2
     1793050.047      278451.895     1792887.318      280005.892
#Sta/Elev= 30
       0 1135.47      59 1147.33   137.6 1158.63   186.7 1160.32     226 1157.46
   245.7 1154.61   275.2 1144.62   314.5 1125.47   393.1 1077.46   461.9 1032.54
   471.7 1026.65   487.8  1019.9   501.2 1017.45     511 1019.36   530.7  1024.3
   805.8 1024.52   825.5 1026.62   864.8 1034.73   874.6 1035.72   913.9 1034.79
   943.4 1029.91   953.2 1029.42    1022 1032.15  1051.5 1035.46  1149.8 1054.23
  1238.2  1066.2  1297.2 1077.14  1356.1 1085.07  1464.2 1093.69  1562.5 1096.52
#Mann= 3 , 0 , 0
       0      .1       0   487.8    .045       0     511     .08       0
Bank Sta=487.8,511
XS Rating Curve= 0 ,0
Exp/Cntr=0.3,0.1

Type RM Length L Ch R = 1 ,2384.8  ,618,619.9,620.5
XS GIS Cut Line= 2
     1792700.204      278441.389     1792544.364      279936.016
#Sta/Elev= 30
       0 1098.32   127.7 1109.96   255.4 1116.05   324.1 1118.16   500.9 1119.79
     550 1123.57   569.7 1122.52   628.6 1112.18   648.2 1106.76   795.6 1045.56
   805.4 1040.42   834.8 1020.29   844.7  1016.2   854.5 1015.42   864.3 1017.45
   903.6 1031.08   923.2 1032.88   952.7 1032.13  1041.1 1025.16    1100 1029.54
  1188.4 1029.15  1198.3 1030.34  1208.1 1034.24  1237.5 1054.78  1247.4 1060.55
  1257.2 1063.57  1316.1  1071.6  1345.6  1073.4  1384.9 1078.44  1502.7 1080.98
#Mann= 3 , 0 , 0
       0      .1       0   834.8    .045       0   864.3      .1       0
Bank Sta=834.8,864.3
XS Rating Curve= 0 ,0
Exp/Cntr=0.3,0.1

Type RM Length L Ch R = 1 ,1764.9  ,263.7,264.8,265.6
XS GIS Cut Line= 2
     1792231.004      278409.181     1792082.053      279844.439
#Sta/Elev= 30
       0 1070.25    39.3 1070.53   137.4 1076.17   206.1 1078.02     265 1078.38
   314.1 1076.32   441.7 1080.21   530.1 1077.51   579.2  1070.9     589 1068.38
   598.8 1063.21   647.9 1021.87   657.7 1016.26   660.9 1015.72   667.5  1014.6
   687.1  1014.6   785.3  1021.9   912.9 1023.73   932.5 1026.23   952.2 1031.58
  1079.8  1041.2  1109.2 1046.34  1148.5  1056.2  1217.2 1063.72    1227 1066.19
  1246.6 1078.48  1256.5 1080.37  1295.7 1081.56  1403.7 1093.52    1443 1100.24
#Mann= 3 , 0 , 0
       0      .1       0   660.9    .045       0   687.1      .1       0
Bank Sta=660.9,687.1
XS Rating Curve= 0 ,0
Exp/Cntr=0.3,0.1

Type RM Length L Ch R = 1 ,1500.1  ,365.6,359.8,383.5
XS GIS Cut Line= 2
     1791994.199      278413.372     1791795.322      279814.352
#Sta/Elev= 30
       0  1067.1    29.5 1064.84   127.8 1047.85   147.4 1049.69   196.5 1060.76
   255.5 1067.73   334.1 1072.02   412.7 1070.11   589.6 1047.28   599.4 1044.72
   609.2 1039.11   628.9 1022.81   638.7 1016.97   648.6 1014.79   658.4  1014.6
   674.5  1014.6   727.2 1014.66   864.7  1019.6   894.2 1023.28   923.7 1031.41
    1022 1038.09  1031.8 1039.87  1071.1 1054.93  1100.6 1058.51  1159.5 1082.98
    1189 1091.88    1248 1095.35  1277.4  1102.6  1297.1 1104.99    1415  1112.8
#Mann= 3 , 0 , 0
       0      .1       0   648.6    .045       0   674.5     .06       0
Bank Sta=648.6,674.5
XS Rating Curve= 0 ,0
Exp/Cntr=0.3,0.1

Type RM Length L Ch R = 1 ,1140.3  ,671.7,670.6,668.8
XS GIS Cut Line= 2
     1791656.161      278322.651     1791445.474      279824.672
#Sta/Elev= 30
       0 1075.64   166.4  1073.7   381.6 1073.65   450.1  1060.1   567.6 1044.86
   577.3 1041.61   606.7 1025.09   616.5 1021.03   626.3 1019.01   655.6  1018.4
   694.8 1015.41   763.3  1014.7   793.6 1014.42   861.1 1013.72   919.8 1017.06
   929.6 1018.42     959  1028.7   968.8 1030.28  1017.7 1032.66  1037.2 1038.28
  1076.4 1053.93  1086.2 1056.93    1096  1058.3  1135.1 1060.68  1223.2 1068.47
  1272.1 1076.21  1301.4 1082.72  1360.2 1090.26    1458 1093.74  1516.7 1099.11
#Mann= 3 , 0 , 0
       0     .06       0   763.3    .045       0   793.6     .08       0
Bank Sta=763.3,793.6
XS Rating Curve= 0 ,0
Exp/Cntr=0.3,0.1

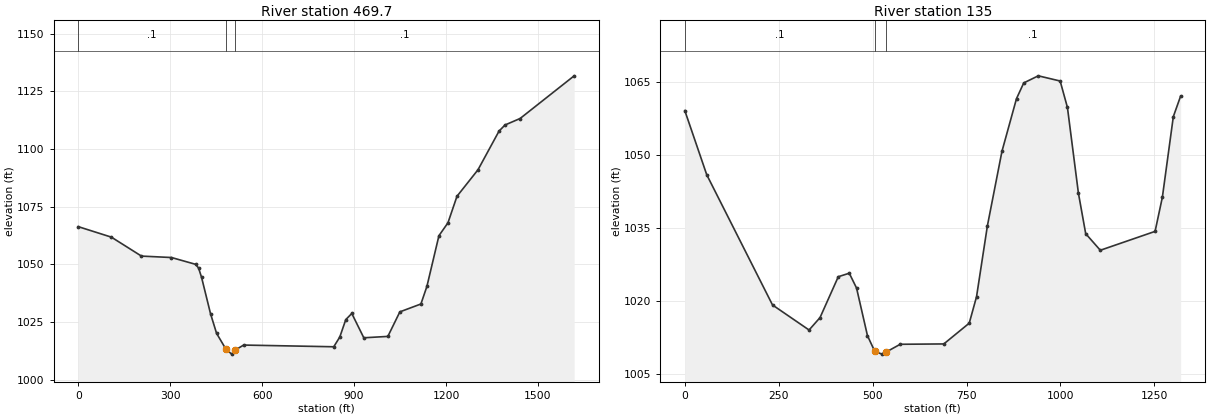
Type RM Length L Ch R = 1 ,469.7   ,329.4,334.7,354.8
XS GIS Cut Line= 2
     1791318.123      278231.929     1791095.627      279834.993
#Sta/Elev= 30
       0 1066.39   107.9 1061.85     206 1053.64   304.1 1053.02   382.5 1050.08
   392.4 1048.49   402.2 1044.44   431.6 1028.62   451.2 1020.17   480.6 1013.55
   500.2 1011.15     510 1012.75   539.5 1015.08   833.7 1014.34   853.4 1018.56
     873 1026.12   892.6 1028.77   931.8 1018.23  1010.3 1018.83  1049.5 1029.47
  1118.2 1032.88  1137.8 1040.52    1177 1062.47  1206.5 1068.08  1235.9 1079.56
  1304.6 1091.07  1373.2 1107.82  1392.8 1110.47  1441.9 1113.27  1618.4 1131.77
#Mann= 3 , 0 , 0
       0      .1       0   480.6    .045       0     510      .1       0
Bank Sta=480.6,510
XS Rating Curve= 0 ,0
Exp/Cntr=0.3,0.1

Type RM Length L Ch R = 1 ,135     ,162.5,135,92.4
XS GIS Cut Line= 4
     1791197.179       278212.66      1790943.96      278605.009
     1790896.656      279105.881     1791024.656      279431.448
#Sta/Elev= 30
       0 1059.18    58.4 1045.96   233.5 1019.13   330.8 1013.97     360 1016.53
   408.6 1024.95   437.8 1025.67   457.2 1022.62   486.3 1012.79   505.7 1009.57
     525    1009   534.7 1009.37   573.4 1011.03   689.5  1011.1   757.2 1015.38
   776.6 1020.82   805.6 1035.47   844.3 1050.79     883 1061.64   902.3 1064.88
     941 1066.34   999.2 1065.27  1018.6 1059.82  1047.8 1042.17  1067.2 1033.82
  1106.1  1030.4  1251.9 1034.29  1271.3 1041.32  1300.5 1057.94  1319.9 1062.16
#Mann= 3 , 0 , 0
       0      .1       0   505.7    .045       0   534.7      .1       0
Bank Sta=505.7,534.7
XS Rating Curve= 0 ,0
Exp/Cntr=0.3,0.1

Chan Stop Cuts=-1
Use User Specified Reach Order=0
Composite Channel Slope=5